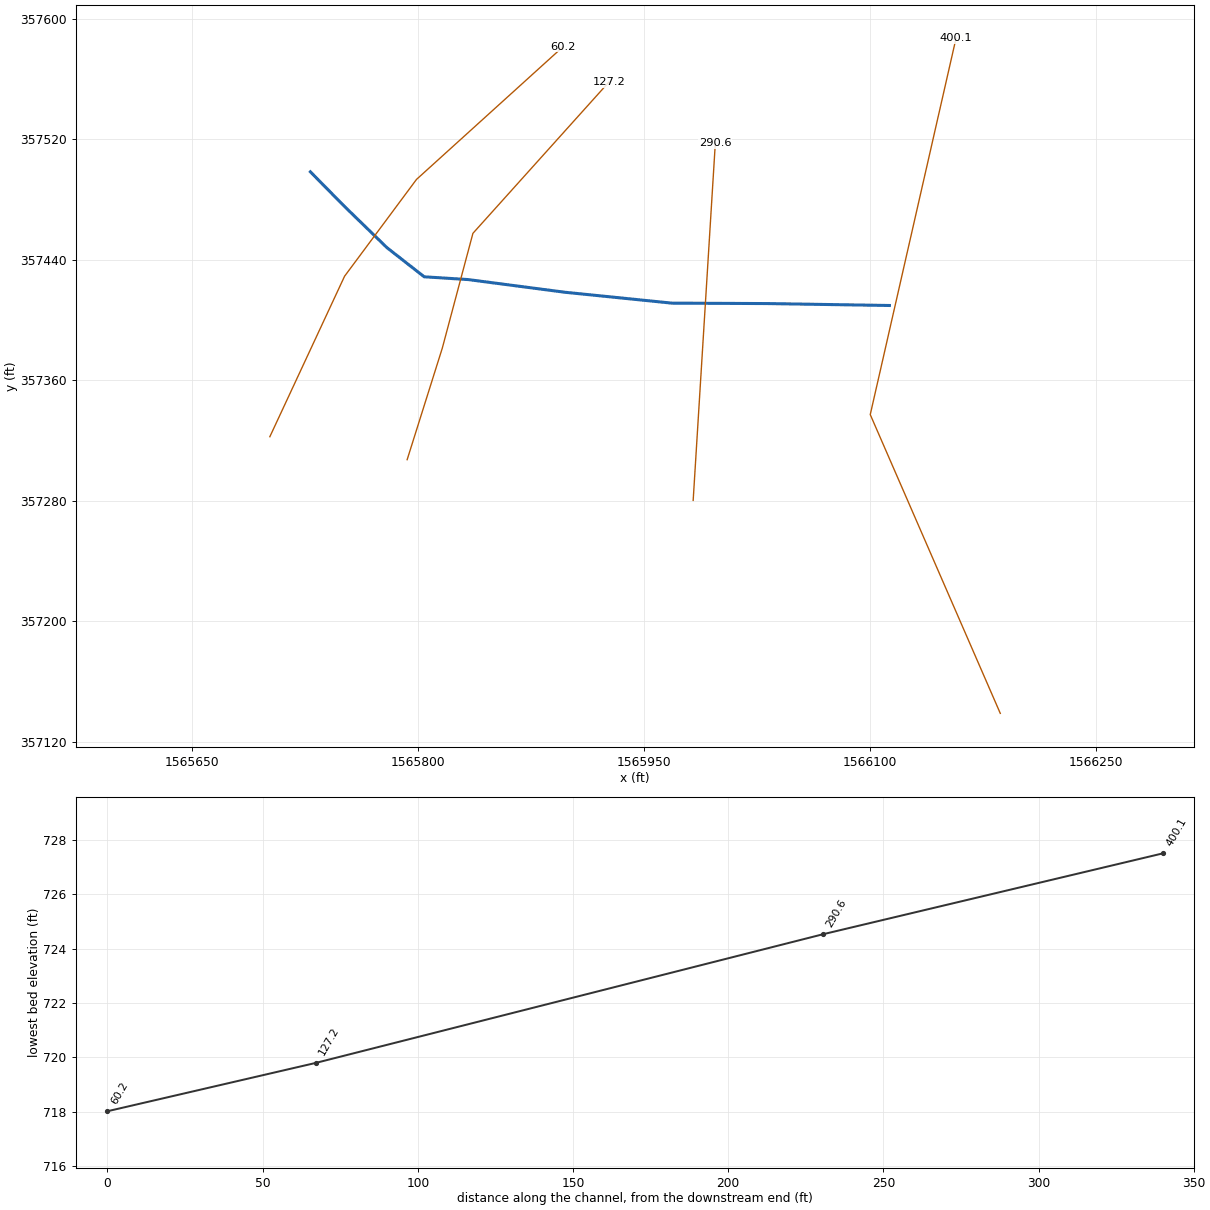
--- JONNIESBR.prj (project) ---

Proj Title=JONNIESBR
Current Plan=p01
Default Exp/Contr=0,0
English Units
Geom File=g01
Flow File=f01
Plan File=p01
BEGIN DESCRIPTION:
END DESCRIPTION:
DSS Export Rating Curves= 0
DSS Export Rating Curve Sorted= 0
DSS Export Volume Flow Curves= 0
DXF OffsetX= 0
DXF OffsetY= 0
DXF ScaleX= 0
DXF ScaleY= 0

--- JONNIESBR.p01 (plan) ---

Plan Title=Floodplain
Program Version=4.00
Geom File=g01
Flow File=f01
K Sum by GR=0
Std Step Tol=0.01
Critical Tol=0.01
Num of Std Step Trials=20
Max Error Tol=0.3
Flow Tol Ratio=0.001
Split Flow NTrial=30
Split Flow Tol=0.02
Split Flow Ratio=0.02
Log Output Level=0
Friction Slope Method=1
Unsteady Friction Slope Method=2
Unsteady Bridges Friction Slope Method=1
Global Log Level=0
CheckData=False
Run HTab=0
Run UNet=0
Run PostProcess=0
UNET Theta=0
UNET Theta Warmup=0
UNET ZTol=0
UNET ZSATol=0
UNET MxIter=0
UNET MaxInSteps=0
UNET DtIC=0
UNET DtMin=0
UNET MaxCRTS=0
UNET WFStab=0
UNET SFStab=0
UNET WFX=0
UNET SFX=0
UNET DSS MLevel=0
UNET DZMax Abort=0
UNET Convert EG Bridges=0
UNET Use Existing IB Tables=0
UNET Froude Limit=0
UNET Froude Power=0
Write IC File=0
Echo Input=False
Echo Output=False
Write Detailed=0

--- JONNIESBR.f01 (steady flow) ---

Flow Title=NFF Regression Equation
Program Version=4.00
Number of Profiles= 1
Profile Names=P100yr
River Rch & RM=JONNIESBR,Main            ,400.1
     355
River Rch & RM=JONNIESBR,Main            ,290.6
357.6627
Boundary for River Rch & Prof#=JONNIESBR,Main            , 1
Up Type= 0
Dn Type= 3
Dn Slope=0.019
DSS Import GetInterval= 0
DSS Import GetPeak= 0
DSS Import FillOption= 0

--- JONNIESBR.g01 (geometry) ---

Geom Title=Geometry
Program Version=4.00

River Reach=JONNIESBR       ,Main
Reach XY= 9
     1566113.152      357409.663     1566032.755      357410.935
     1565968.726      357411.228     1565897.601      357418.466
     1565833.405      357426.882     1565804.243      357428.725
     1565779.501      357448.085     1565751.162      357475.618
     1565728.696      357498.423

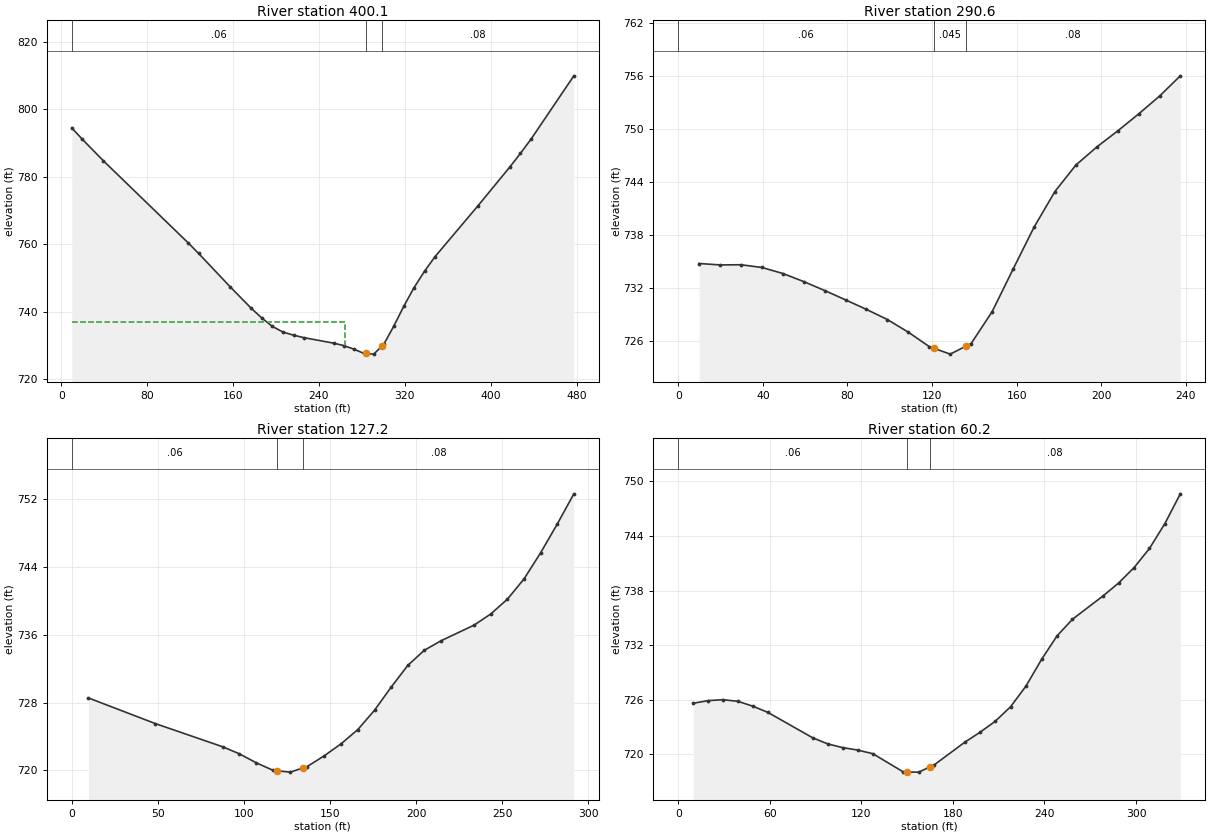
Type RM Length L Ch R = 1 ,400.1   ,110.9,109.5,108.1
XS GIS Cut Line= 3
     1566186.772      357138.811     1566100.428       357337.22
     1566157.378      357587.069
#Sta/Elev= 30
     9.8  794.48    19.7   791.1    39.3  784.73     118  760.52   127.9  757.35
   157.4  747.42     177  741.08   186.9  738.18   196.7  735.71   206.5  734.05
   216.4  733.12   225.7  732.41   253.7  730.76   263.1  730.05   272.4  729.01
   281.8  727.74   283.6   727.7   291.1  727.51   298.6  729.85   300.4  730.41
   309.8  735.81   319.1  741.68   328.4  747.07   338.4  752.06   348.3  756.41
   388.1  771.39   417.9  782.92   427.8  786.96   437.8  791.24   477.5   809.9
#Mann= 3 , 0 , 0
     9.8     .06       0   283.6    .045       0   298.6     .08       0
#XS Ineff= 2 , 0
          264.13  737.13
Permanent Ineff=
       F       F
Bank Sta=283.6,298.6
XS Rating Curve= 0 ,0
Exp/Cntr=0.3,0.1

Type RM Length L Ch R = 1 ,290.6   ,167.9,163.4,158.9
XS GIS Cut Line= 2
     1565982.851       357280.27     1565997.548      357517.259
#Sta/Elev= 26
     9.9  734.78    19.8  734.62    29.7  734.64    39.6  734.33    49.5  733.65
    59.4  732.73    69.3  731.72    79.1  730.67      89  729.59    98.9  728.44
   108.8  727.01   118.7  725.38   121.1  725.17   128.6  724.53   136.1  725.44
   138.5  725.73   148.4  729.32   158.3  734.13   168.2  738.87   178.1  742.92
     188  745.91   197.9  747.96   207.8  749.78   217.7   751.7   227.6  753.72
   237.4  756.01
#Mann= 3 , 0 , 0
       0     .06       0   121.1    .045       0   136.1     .08       0
Bank Sta=121.1,136.1
XS Rating Curve= 0 ,0
Exp/Cntr=0.3,0.1

Type RM Length L Ch R = 1 ,127.2   ,75.9,67.1,58.2
XS GIS Cut Line= 4
     1565792.939      357307.288     1565816.295      357381.418
     1565836.605       357457.58     1565926.983      357558.113
#Sta/Elev= 25
     9.7  728.55    48.6  725.52    87.6  722.79    97.4  721.95   107.3  720.88
   117.1  719.99   119.5  719.94     127  719.79   134.5   720.3   136.8  720.45
   146.7  721.72   156.5  723.14   166.2  724.82   175.9   727.1   185.5  729.81
   195.2  732.39   204.8  734.18   214.5   735.3   233.8  737.16   243.5  738.48
   253.1  740.22   262.8  742.62   272.4   745.7   282.1   749.1   291.7  752.66
#Mann= 3 , 0 , 0
       0     .06       0   119.5    .045       0   134.5     .08       0
Bank Sta=119.5,134.5
XS Rating Curve= 0 ,0
Exp/Cntr=0.3,0.1

Type RM Length L Ch R = 1 ,60.2    ,63.7,60.2,56.7
XS GIS Cut Line= 4
     1565701.771      357322.523     1565751.374      357429.077
     1565799.139      357493.376     1565896.507      357581.558
#Sta/Elev= 30
     9.8  725.59    19.6  725.88    29.4  725.98    39.2   725.8      49  725.26
    58.8  724.58    88.1  721.79    97.9  721.12   107.7  720.71   117.5  720.44
   127.5  720.04   147.6  718.02   150.1  718.02   157.6  718.01   165.1   718.6
   167.6  718.79   187.6  721.28   197.6  722.38   207.7   723.6   217.8  725.21
   227.9  727.49   238.1  730.42   248.2     733   258.3  734.83   278.5  737.42
   288.6  738.83   298.7  740.52   308.8  742.63   318.9  745.37     329  748.64
#Mann= 3 , 0 , 0
       0     .06       0   150.1    .045       0   165.1     .08       0
Bank Sta=150.1,165.1
XS Rating Curve= 0 ,0
Exp/Cntr=0.3,0.1

Chan Stop Cuts=-1
Use User Specified Reach Order=0